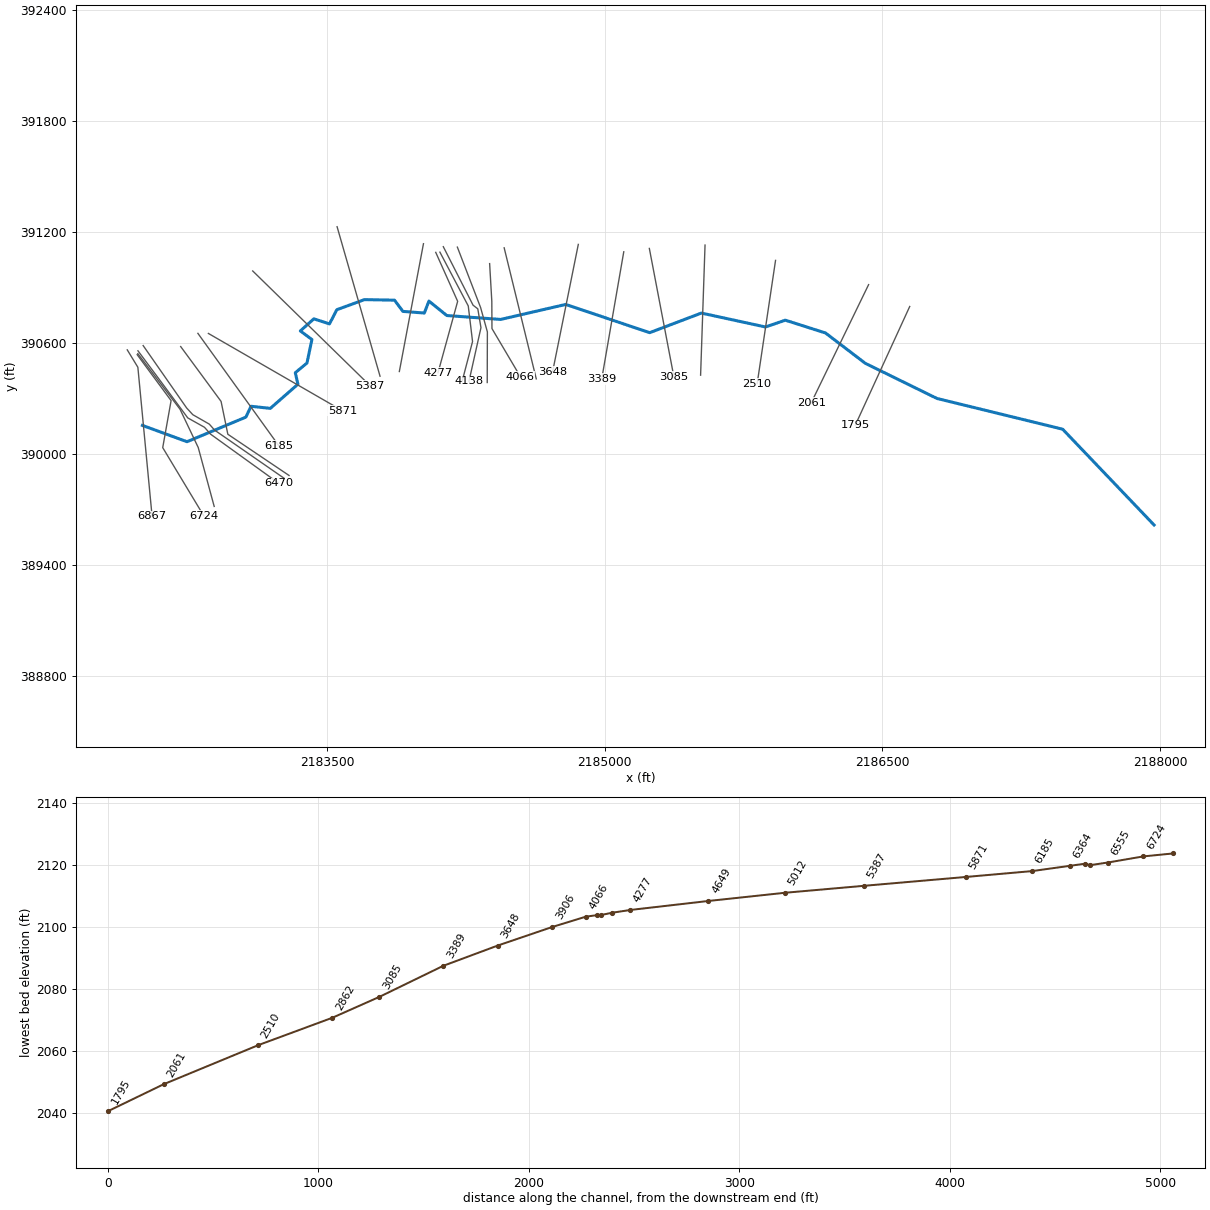
--- TRMPRN.prj (project) ---

Proj Title=TRMPRN
Current Plan=p01
Default Exp/Contr=0,0
English Units
Geom File=g01
Flow File=f01
Plan File=p01
Background Map Layer=Inundation Boundary (01pct Value_0)
Background Map Layer=Inundation Boundary (01pct Value_0)
BEGIN DESCRIPTION:
----------MODEL BY WOOD PLC 2021----------
Stream Name: Trump Run
Flood Zone: Enhanced Approximate
Pocahontas County, WV
HEC-RAS Version: RAS 6.1
Vertical Datum: NAVD88
Projection: NAD 1983 StatePlane West Virginia S FIPS 4702 (US Feet)
Terrain: 1-meter LIDAR (FEMA Region III 3DEP collected 2016-2018)
Land Use: 2019 NLCD
Hydrologic Method:
WV SIR2010-5033 regression equations
Model Notes:
Normal depth tie in to Locust Creek
END DESCRIPTION:
DSS Export Rating Curves= 0
DSS Export Rating Curve Sorted= 0
DSS Export Volume Flow Curves= 0
DXF OffsetX= 0
DXF OffsetY= 0
DXF ScaleX= 0
DXF ScaleY= 0

--- TRMPRN.p01 (plan) ---

Plan Title=Floodplain
Program Version=6.00
Short Identifier=Floodplain
Geom File=g01
Flow File=f01
Subcritical Flow
K Sum by GR= 0
Std Step Tol= 0.01
Critical Tol= 0.01
Num of Std Step Trials= 20
Max Error Tol= 0.3
Flow Tol Ratio= 0.001
Split Flow NTrial= 30
Split Flow Tol= 0.02
Split Flow Ratio= 0.02
Log Output Level= 0
Friction Slope Method= 1
Unsteady Friction Slope Method= 2
Unsteady Bridges Friction Slope Method= 1
Parabolic Critical Depth
Global Vel Dist= 0 , 0 , 0
Global Log Level= 0
CheckData=False
Encroach Param=-1 ,0,0, 0
Mapping Interval=1HOUR
Computation Time Step Use Courant=        0
Computation Time Step Use Time Series=    0
Computation Time Step Count To Double=0
Computation Time Step Max Doubling=0
Computation Time Step Max Halving=0
Computation Time Step Residence Courant=0
Run HTab= 0
Run UNet= 0
Run Sediment= 0
Run PostProcess= 0
Run WQNet= 0
Run RASMapper=-1
UNET Theta= 0
UNET Theta Warmup= 0
UNET ZTol= 0
UNET ZSATol= 0
UNET MxIter= 0
UNET Max Iter WO Improvement= 0
UNET MaxInSteps= 0
UNET DtIC= 0
UNET DtMin= 0
UNET MaxCRTS= 0
UNET WFStab= 0
UNET SFStab= 0
UNET WFX= 1
UNET SFX= 1
UNET Gravity=32.174
UNET 1D Methodology=Finite Difference
UNET DSS MLevel= 1
UNET Pardiso=0
UNET DZMax Abort= 0
UNET Use Existing IB Tables= 0
UNET Froude Reduction=False
UNET Froude Limit= 0
UNET Froude Power= 0
UNET D1 Cores= 0
UNET WindReference=Eulerian
UNET WindDragFormulation=Hsu (1988)
UNET D2 Coriolis=0
UNET D2 Cores= 0
UNET D2 Theta= 1
UNET D2 Theta Warmup= 1
UNET D2 Z Tol= 0.01
UNET D2 Volume Tol= 0.01
UNET D2 Max Iterations= 20
UNET D2 Equation= 0
UNET D2 RampUpFraction=0.1
UNET D2 TimeSlices= 1
UNET D2 Turbulence Formulation=Non-Conservative (original)
UNET D2 Eddy Viscosity=0.3
UNET D2 Transverse Eddy Viscosity=0.1
UNET D2 Smagorinsky Mixing=0
UNET D2 BCVolumeCheck=0
UNET D2 Cores=0
UNET D2 SolverType=PARDISO (Direct)
UNET D2 Minimum Iterations= 2147483647
UNET D2 Maximum Iterations= 2147483647
UNET D2 Restart Number= 10
UNET D2 Relaxation Coeff=1.3
UNET D2 SOR Precondition Iterations= 10
UNET D2 ILUT Maximum Fill= 8
UNET D2 ILUT Tolerance=1E-08
UNET D1D2 MaxIter= 0
UNET D1D2 ZTol=0.01
UNET D1D2 QTol=0.1
UNET D1D2 MinQTol=1
Write IC File= 0
Write IC File at Fixed DateTime=0
Write IC File at Sim End=0
Echo Input=False
Echo Parameters=False
Echo Output=False
Write Detailed= 0
HDF Write Warmup=0
HDF Write Time Slices=0
HDF Flush=0
HDF Compression= 1
HDF Chunk Size= 1
HDF Spatial Parts= 1
HDF Use Max Rows=0
HDF Fixed Rows= 1
Calibration Method= 0
Calibration Iterations= 20
Calibration Max Change=0.05
Calibration Tolerance=0.2
Calibration Maximum=1.5
Calibration Minimum=0.5
Calibration Optimization Method= 1
WQ AD Non Conservative
WQ ULTIMATE=-1
WQ Max Comp Step=1HOUR
WQ Output Interval=15MIN
WQ Output Selected Increments= 0
WQ Output face flow=0
WQ Output face velocity=0
WQ Output face area=0
WQ Output face dispersion=0
WQ Output cell volume=0
WQ Output cell surface area=0
WQ Output cell continuity=0
WQ Output cumulative cell continuity=0
WQ Output face conc=0
WQ Output face dconc_dx=0
WQ Output face courant=0
WQ Output face peclet=0
WQ Output face adv mass=0
WQ Output face disp mass=0
WQ Output cell mass=0
WQ Output cell source sink temp=0
WQ Output nsm pathways=0
WQ Output nsm derived pathways=0
WQ Create Restart=0
WQ Fixed Restart=0
WQ System Summary=0
WQ Write To DSS=0
Sorting and Armoring Iterations= 10
XS Update Threshold= 0.02
Bed Roughness Predictor= 0
Hydraulics Update Threshold= 0.02
Energy Slope Method= 1
Volume Change Method= 1
Sediment Retention Method= 0
Sediment TS Multiplier= 1
Warm Up Method= 0
XS Weighting Method= 0
Number of US Weighted Cross Sections= 1
Number of DS Weighted Cross Sections= 1
Upstream XS Weight=0
Main XS Weight=1
Downstream XS Weight=0
Number of DS XS's Weighted with US Boundary= 1
Upstream Boundary Weight= 1
Weight of XSs Associated with US Boundary= 0
Number of US XS's Weighted with DS Boundary= 1
Downstream Boundary Weight= 0.5
Weight of XSs Associated with DS Boundary= 0.5
Percentile Method= 0
Sediment Output Level= 3
Mass or Volume Output= 0
Output Increment Type= 1
Profile and TS Output Increment= 1
Transport Output Increment 1
XS Output Flag= 0
XS Output Increment= 10
Read HDF5 Sediment Hotstart= 0
Sediment Hotstart Type= 0
Write Gradation File= 0
Read Gradation Hotstart= 0
Write HDF5 File= 1
Write Binary Output= 1
Write DSS Sediment File= 0
DSS Sediment Output Type= 1
SV Curve= 0
Specific Gage Flag= 0
Subcell Erosion Methods= 0
Subcell Deposition Methods= 0
Advection Scheme= 1
Matrix Solver= 0
Implicit Weighting Factor= 1
Maximum Outer Loop Convergence Iterations= 5
Convergence Maximum Absolute= 0.001
Convergence RMSE= 0.0001
Grain Fractions Max Abs Error= 0.001
Max Subgrid Regions= 1
Max Subgrid Length Scale= 3.402823E+38
Initial Layer Thickness= 3.402823E+38
Min Layer Thickness= 3.402823E+38
Max Layer Thickness= 3.402823E+38
Number of Layers= 5

--- TRMPRN.f01 (steady flow) ---

Flow Title=Flow
Program Version=6.00
Number of Profiles= 6
Profile Names=01pct,10pct,04pct,02pct,0_2pct,01plus
River Rch & RM=TRMPRN,Main,6867
     808     433     572     686    1120    1190
Boundary for River Rch & Prof#=TRMPRN,Main            , 1
Up Type= 0
Dn Type= 3
Dn Slope=0.02238
Boundary for River Rch & Prof#=TRMPRN,Main            , 2
Up Type= 0
Dn Type= 3
Dn Slope=0.02238
Boundary for River Rch & Prof#=TRMPRN,Main            , 3
Up Type= 0
Dn Type= 3
Dn Slope=0.02238
Boundary for River Rch & Prof#=TRMPRN,Main            , 4
Up Type= 0
Dn Type= 3
Dn Slope=0.02238
Boundary for River Rch & Prof#=TRMPRN,Main            , 5
Up Type= 0
Dn Type= 3
Dn Slope=0.02238
Boundary for River Rch & Prof#=TRMPRN,Main            , 6
Up Type= 0
Dn Type= 3
Dn Slope=0.02238
DSS Import GetInterval= 0
DSS Import GetPeak= 0
DSS Import FillOption= 0

--- TRMPRN.g01 (geometry) ---

Geom Title=Geometry
Program Version=6.10

River Reach=TRMPRN          ,Main
Reach XY= 30
2182502.79381984390155.6765004082182743.58984586390067.548057318
     2183061.481      390200.329      2183089.36       390258.91
2183193.52384795390247.6020042672183342.84675292390378.130814118
     2183328.505      390440.143     2183391.442      390492.431
      2183418.27      390619.582     2183355.689      390665.734
     2183428.708      390731.164     2183513.198      390703.895
     2183552.748      390780.374     2183701.849      390834.932
2183864.57166833390831.957827703     2183909.587      390771.394
     2184025.407      390762.479     2184050.195      390827.261
     2184146.567      390749.082     2184437.681      390727.901
     2184789.299      390808.923     2185242.713       390656.47
 2185521.8233608390762.3470488532185867.93862177390687.219441576
     2185975.265      390723.942       2186192.2       390654.86
     2186407.663      390490.6552186794.41314275390301.121430011
2187473.14134962390135.161116539     2187966.975        389617.8

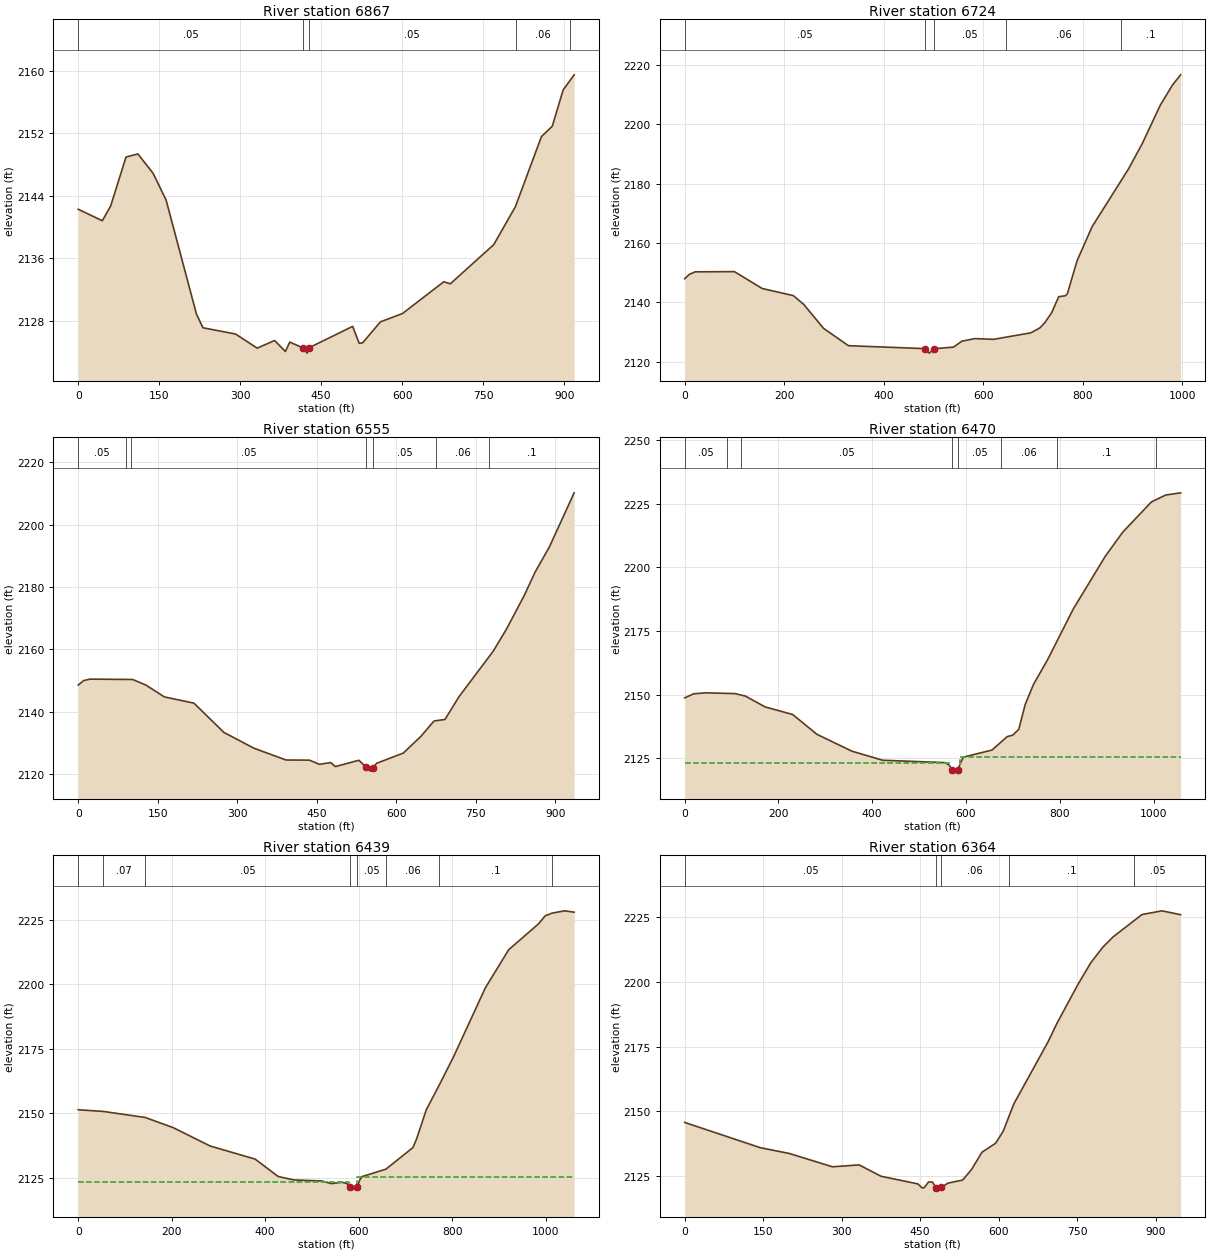
Type RM Length L Ch R = 1 ,6867    ,143.1,143.1,143.1
XS GIS Cut Line= 3
 2182420.8788381390563.5849610752182478.16789301390469.748651978
2182555.01172116389664.859737714
#Sta/Elev= 30
       0 2142.29    44.7 2140.82    60.1 2142.71    88.5 2148.98   110.5 2149.38
   138.6 2146.91   162.8 2143.47     219 2128.85   231.1  2127.1   291.3  2126.3
   331.5 2124.49   363.7 2125.47   383.7 2124.06   391.8 2125.26   416.7 2124.51
   423.9 2123.85 427.0982124.526   508.3 2127.28   520.4 2125.11   526.8 2125.17
   559.8 2127.86   600.7 2128.93   677.1    2133   689.1 2132.73   769.5 2137.75
   809.7 2142.62   857.9  2151.6     878 2152.94   898.1 2157.58   918.5 2159.52
#Mann= 5 ,-1,0
       0     .05       0   416.7    .045       0 427.098     .05       0
  809.94     .06       0  909.94     .05       0
Bank Sta=416.7,427.098
XS Rating Curve= 0 ,0
Exp/Cntr=0.3,0.1

Type RM Length L Ch R = 1 ,6724    ,158.8,168.4,173
XS GIS Cut Line= 4
2182474.51954194390537.607981895 2182657.6667657 390289.52010908
2182612.42721242390035.5948745512182834.24695752389667.111416399
#Sta/Elev= 30
       0 2147.95     9.5 2149.46    21.5 2150.29     100 2150.35   155.9 2144.66
   218.3 2142.27   239.2 2139.31   278.9 2131.25     329 2125.39   483.4 2124.39
   491.5 2122.88   500.82124.354   540.3 2124.91   556.6 2126.89   583.1 2127.78
   620.3 2127.53   695.2 2129.71   713.8  2131.4   723.2 2133.07   737.2 2136.47
   751.5  2141.9   765.2 2142.23     769 2142.99   788.5 2154.08   818.5 2165.48
   891.4 2184.89   919.3  2193.5   955.5 2206.45     980 2213.26   996.4  2216.7
#Mann= 5 ,-1,0
       0     .05       0   483.4    .045       0   500.8     .05       0
  646.29     .06       0  876.29      .1       0
Bank Sta=483.4,500.8
XS Rating Curve= 0 ,0
Exp/Cntr(USF)=0,0
Exp/Cntr=0.5,0.3

Type RM Length L Ch R = 1 ,6555    ,80.6,85.5,86.8
BEGIN DESCRIPTION:
structure xs 4
END DESCRIPTION:
XS GIS Cut Line= 4
2182477.98643784390542.9033684032182705.76129341390243.275246089
2182804.20026885390036.3378378722182890.42418894389718.027866204
#Sta/Elev= 30
       0 2148.52    10.2 2149.96    22.3 2150.42   102.7 2150.31   127.8  2148.5
   162.6 2144.71   218.2 2142.72   274.6 2133.35   331.1 2128.28     392 2124.48
   436.3 2124.43   454.8 2123.09   476.1 2123.66     485 2122.37   529.3  2124.4
   542.8 2122.21   551.4 2120.91   555.32121.926   562.9 2123.43     613 2126.69
   646.1 2132.03     671 2136.99   691.7 2137.49     718 2144.75   782.9 2159.44
   807.7 2166.48   840.9 2177.15   861.6 2184.73   888.6 2192.82   935.3 2210.18
#Mann= 7 ,-1,0
       0     .05       0      90     .07       0     100     .05       0
   542.8    .045       0   555.3     .05       0  675.53     .06       0
  775.53      .1       0
Bank Sta=542.8,555.3
XS Rating Curve= 0 ,0
Exp/Cntr(USF)=0,0
Exp/Cntr=0.3,0.1

Type RM Length L Ch R = 1 ,6470    ,21.3,21.5,21.2
BEGIN DESCRIPTION:
structure xs 3; 4.4 ft between structure & xs
END DESCRIPTION:
XS GIS Cut Line= 6
2182478.66406876390558.5568137442182582.68585449390419.073055605
2182747.58402619390196.2536623062182838.01205583390145.424835187
2182871.10989674390108.1897641582183238.73234404389843.407036843
#Sta/Elev= 30
       0 2148.81    19.2  2150.4    44.9 2150.79   107.8 2150.47   129.7 2149.49
   171.4 2145.26   230.3 2142.28   282.2 2134.49   356.6 2127.88   422.4 2124.31
   554.9 2123.39   564.2 2122.41   570.2 2120.57   576.3 2120.04   582.3 2120.55
   592.7 2124.96   596.3 2125.62   655.4 2128.31   687.9 2133.58   699.7 2134.16
   712.6 2136.45   726.3 2146.21   744.1 2154.13   774.2 2163.84   828.9 2183.71
   896.9 2204.34   934.3 2213.85   995.5 2225.74    1026 2228.44  1057.8 2229.31
#Mann= 8 ,-1,0
       0     .05       0      90     .07       0     120     .05       0
   570.2    .045       0   582.3     .05       0  674.75     .06       0
  794.75      .1       0 1004.75     .05       0
#XS Ineff= 2 , 0
             566 2123.29   586.7         2125.65
Permanent Ineff=
       F       F
Bank Sta=570.2,582.3
XS Rating Curve= 0 ,0
Exp/Cntr(USF)=0,0
Exp/Cntr=0.5,0.3

Type RM Length L Ch R = 1 ,6439    ,84.1,74.5,72.3
BEGIN DESCRIPTION:
structure xs 2; 3ft between structure & xs
END DESCRIPTION:
XS GIS Cut Line= 6
2182506.77971121390586.7075364462182741.57112518390249.859773574
2182774.84627595390213.5703551432182863.91492999390162.623321449
2182892.63912764390130.1756166962183266.78037286389871.053810746
#Sta/Elev= 30
       0  2151.3    53.8 2150.65   143.3 2148.31   203.2 2144.37   282.2 2137.26
   378.5 2132.17   427.8 2125.43   461.4  2124.1   521.3  2123.7   541.2 2122.68
   564.4 2123.19     575 2122.67   580.4 2121.35   585.7 2120.54   596.4 2121.41
   603.3 2124.47   607.6 2125.42   658.2 2128.27   715.9 2136.63   723.7 2139.91
   744.5 2151.25   772.3 2160.86   803.4 2172.02   870.9 2198.53   920.8 2213.31
   984.4  2223.3   999.1 2226.49  1013.7 2227.51  1040.3  2228.4  1060.9 2227.88
#Mann= 8 ,-1,0
       0     .05       0    53.8     .07       0   143.3     .05       0
   580.4    .045       0   596.4     .05       0   658.2     .06       0
   772.3      .1       0  1013.7     .05       0
#XS Ineff= 2 , 0
           579.4 2123.29   597.4          2125.1
Permanent Ineff=
       F       F
Bank Sta=580.4,596.4
XS Rating Curve= 0 ,0
Exp/Cntr(USF)=0,0
Exp/Cntr=0.5,0.3

Type RM Length L Ch R = 1 ,6364    ,175,179.6,183.8
BEGIN DESCRIPTION:
structure xs 1
END DESCRIPTION:
XS GIS Cut Line= 4
 2182709.4733509390581.3881947452182927.64474494390285.142087795
2182964.12825564390107.8322257532183294.66886266389885.282810434
#Sta/Elev= 30
       0 2145.65   144.3 2135.88   200.2 2133.62   282.4 2128.47   333.1 2129.22
   375.1 2124.81   445.5 2121.85   453.6 2120.31   457.7 2120.42   465.9 2122.61
   473.3 2122.58   480.1 2120.46   483.5 2119.83   490.6 2120.47   502.6 2122.14
   530.9 2123.34   547.6 2127.32     568 2134.12   594.1 2137.61   608.5 2142.26
   628.7 2152.79   693.7 2176.67   711.3 2184.06   751.5 2199.17   775.7 2207.42
   798.7 2213.47   818.7 2217.53   873.6 2226.13   911.8 2227.57   947.4 2226.07
#Mann= 5 ,-1,0
       0     .05       0   480.1    .045       0   490.6     .06       0
  618.94      .1       0  858.94     .05       0
Bank Sta=480.1,490.6
XS Rating Curve= 0 ,0
Exp/Cntr(USF)=0,0
Exp/Cntr=0.3,0.1

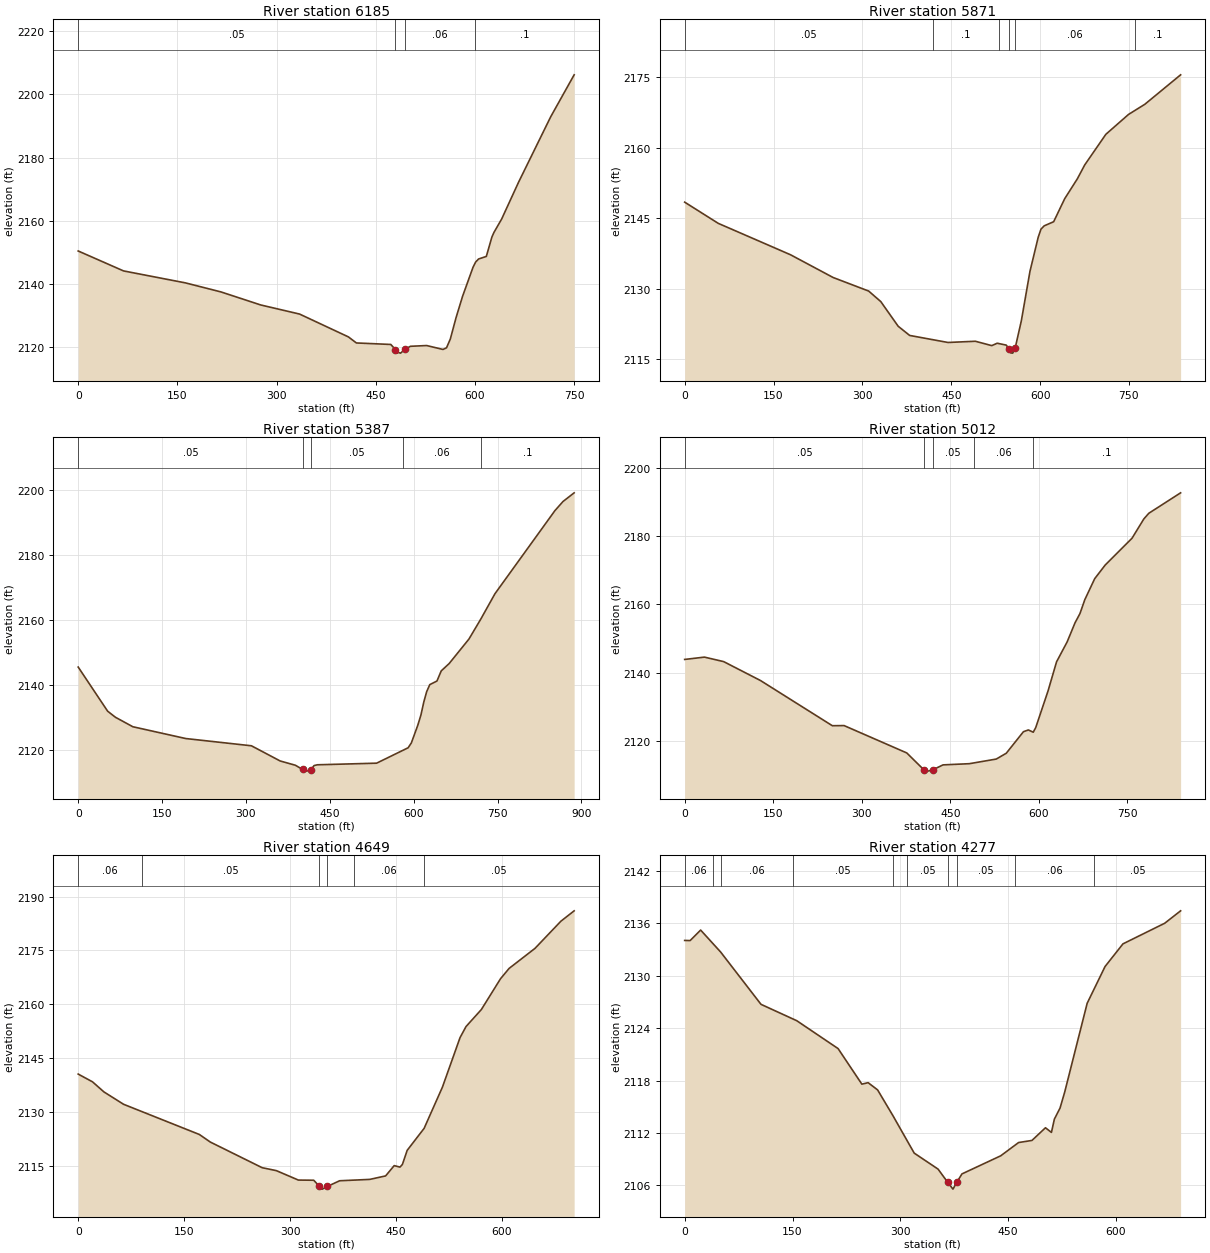
Type RM Length L Ch R = 1 ,6185    ,308,314.1,316.4
XS GIS Cut Line= 2
2182802.39063102390652.7856418772183240.60685041390044.250567987
#Sta/Elev= 30
       0 2150.44    68.5 2144.14   162.2 2140.35   215.9 2137.49   276.1 2133.36
   334.7 2130.49   408.6 2123.26   420.6 2121.35   472.7 2120.87   479.6 2119.27
   482.4 2118.39   487.5 2118.13   493.9 2119.33   502.3 2120.29   526.9 2120.53
   551.6 2119.29   556.9 2119.81   562.7 2122.61   571.3 2129.34   581.2 2136.12
     597  2145.3   600.9 2146.93   605.4 2147.91   617.1 2148.72   625.5 2154.84
   628.6  2156.3   640.3 2160.56   665.8 2172.17   714.5 2192.92   749.9 2206.17
#Mann= 4 ,-1,0
       0     .05       0   479.6    .045       0   493.9     .06       0
     600      .1       0
Bank Sta=479.6,493.9
XS Rating Curve= 0 ,0
Exp/Cntr(USF)=0,0
Exp/Cntr=0.3,0.1

Type RM Length L Ch R = 1 ,5871    ,482.1,483.9,473.9
XS GIS Cut Line= 2
  2182859.093164390652.2741639952183584.41234599390234.145296985
#Sta/Elev= 30
       0 2148.42    56.7  2143.9   178.8  2137.2   250.6 2132.36   310.6 2129.47
   331.1 2127.22   360.4 2121.97   379.8 2120.01   444.5 2118.51   490.7 2118.77
   518.4 2117.84   527.6 2118.35   542.8 2117.95   547.8 2117.13   550.7 2116.28
   553.7 2116.24  557.752117.234   568.3 2123.11   582.9 2133.68   596.8 2140.94
   601.5 2142.67   606.9 2143.37   622.9 2144.25   641.5 2149.15   662.9  2153.4
   675.3 2156.35     711 2162.88   749.2 2167.11   776.9 2169.29   837.2 2175.56
#Mann= 6 ,-1,0
       0     .05       0     420      .1       0     530     .06       0
   547.8    .045       0  557.75     .06       0     760      .1       0
Bank Sta=547.8,557.75
XS Rating Curve= 0 ,0
Exp/Cntr=0.3,0.1

Type RM Length L Ch R = 1 ,5387    ,376.5,374.2,366.2
XS GIS Cut Line= 2
2183098.56288968390989.692359583 2183732.8089566390369.574878672
#Sta/Elev= 30
       0 2145.45    52.6 2131.86    66.6 2129.98    97.7 2127.06   192.5 2123.42
   309.8 2121.19   361.2 2116.51   388.3  2115.2   401.3 2113.91   408.8 2113.38
   416.2 2113.87   421.8 2115.08   427.4 2115.33   533.7 2115.83   590.1 2120.58
   595.8 2122.06   607.2 2127.44     613  2130.7   618.1 2134.68   623.2 2137.86
   628.8 2140.04   641.6 2141.15   649.3 2144.28   663.4 2146.53   698.8 2154.08
     720 2160.23   745.4 2168.07   852.6 2193.67   867.1 2196.49     887 2199.16
#Mann= 5 ,-1,0
       0     .05       0   401.3    .045       0   416.2     .05       0
     580     .06       0     720      .1       0
Bank Sta=401.3,416.2
XS Rating Curve= 0 ,0
Exp/Cntr=0.3,0.1

Type RM Length L Ch R = 1 ,5012    ,365.7,363.9,357.1
XS GIS Cut Line= 2
2183554.22820121 391228.667287042183786.18307277390421.343837953
#Sta/Elev= 30
       0 2143.88    33.5 2144.56    66.1 2143.24   128.5 2137.69   250.1 2124.45
     270 2124.49   376.2 2116.47   405.3  2111.5   411.5 2111.14   419.8 2111.48
   437.6 2112.97   482.2 2113.32   527.8 2114.68   544.7 2116.38   573.8  2122.7
   582.1 2123.21   590.4 2122.55   594.6 2123.91   615.4 2134.62   629.9 2143.19
   647.8 2149.02   661.2 2154.63   669.5 2157.32   677.8 2161.43   694.5 2167.56
   712.4 2171.58   757.7 2179.41   777.7 2185.06   786.1 2186.72     840 2192.72
#Mann= 5 ,-1,0
       0     .05       0   405.3    .045       0   419.8     .05       0
     490     .06       0     590      .1       0
Bank Sta=405.3,419.8
XS Rating Curve= 0 ,0
Exp/Cntr(USF)=0,0
Exp/Cntr=0.3,0.1

Type RM Length L Ch R = 1 ,4649    ,369.4,371.5,364.1
XS GIS Cut Line= 2
2184020.77102374391136.9826958252183890.45344797390446.691907603
#Sta/Elev= 30
       0 2140.55    20.2  2138.4    36.4 2135.59    64.2 2132.14   171.6 2123.72
   187.1 2121.61   260.6 2114.46   280.7 2113.64   311.9 2111.01   333.6 2110.97
   341.7 2109.26   345.8 2108.49     353 2109.25   370.3 2110.82   412.9  2111.2
   435.4 2112.17   447.6 2115.04   455.8 2114.63   459.2 2115.36     466  2119.3
     490 2125.43   515.9 2136.91   540.9 2150.73   549.3 2153.79   571.1 2158.55
   598.2 2167.12   610.4 2170.01     647 2175.58   683.7 2183.15   702.5 2186.05
#Mann= 6 ,-1,0
       0     .06       0      90     .05       0   341.7    .045       0
     353     .05       0     390     .06       0     490     .05       0
Bank Sta=341.7,353
XS Rating Curve= 0 ,0
Exp/Cntr=0.3,0.1

Type RM Length L Ch R = 1 ,4277    ,83.4,88,94
BEGIN DESCRIPTION:
structure xs 4
END DESCRIPTION:
XS GIS Cut Line= 3
2184087.09071524391090.1304829532184205.45943887 390825.82771649
2184099.25188548390439.913247666
#Sta/Elev= 30
       0 2134.03     7.6 2134.02    22.2 2135.22      50 2132.71   106.2 2126.72
   155.9 2124.85   213.4 2121.66   246.5 2117.59   255.2 2117.76   268.4 2116.93
   289.6    2114   319.3  2109.7   352.5 2107.87     366 2106.35   373.2 2105.58
     379 2106.42   385.7 2107.32   439.6 2109.39   464.5 2110.91   483.1 2111.15
   501.9  2112.6   510.2 2112.07   514.3 2113.59   522.2 2114.86   528.7  2116.7
   559.9 2126.84   584.8 2131.05   609.7 2133.64   667.8    2136   689.9 2137.42
#Mann= 10 ,-1,0
       0     .06       0      40     .05       0      50     .06       0
     150     .05       0   289.6     .06       0   309.6     .05       0
     366    .045       0     379     .05       0   459.6     .06       0
   569.6     .05       0
Bank Sta=366,379
XS Rating Curve= 0 ,0
Exp/Cntr(USF)=0,0
Exp/Cntr=0.5,0.3

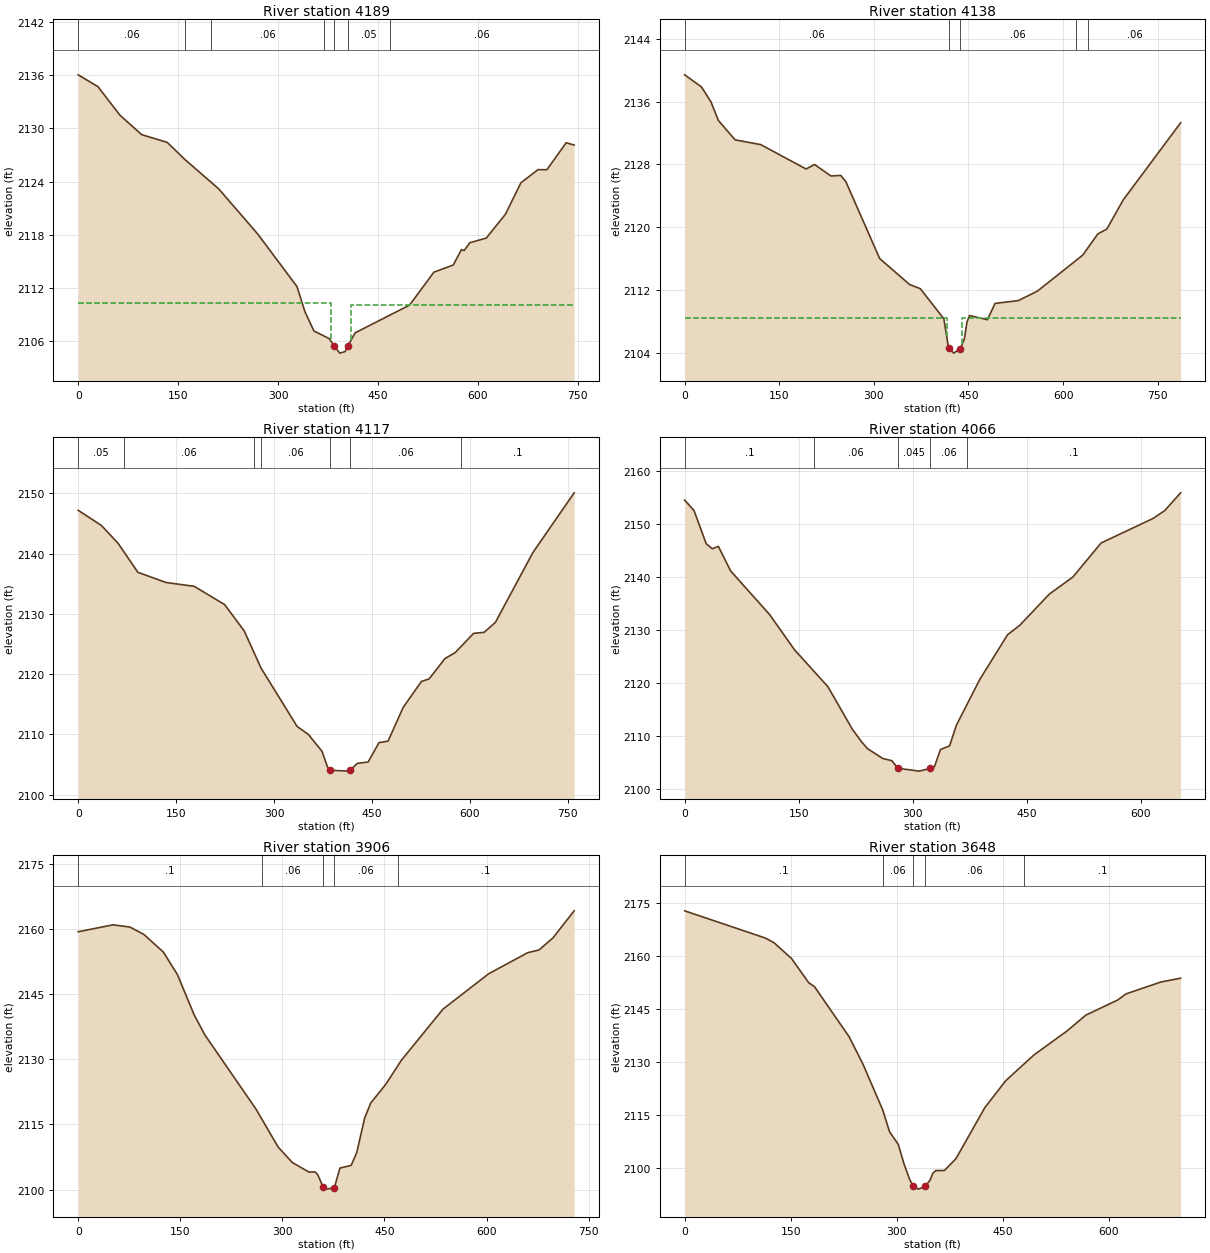
Type RM Length L Ch R = 1 ,4189    ,50.6,51.1,52
BEGIN DESCRIPTION:
structure xs 3; 5.4 ft between structure & xs
END DESCRIPTION:
XS GIS Cut Line= 4
2184109.59830813391091.3733799622184262.70795525390800.814049428
2184285.89444754390608.5276401592184229.61229944390393.595743546
#Sta/Elev= 30
       0 2136.02    29.6 2134.69    62.8 2131.46    95.3 2129.28   133.6 2128.41
     160 2126.49   210.8 2123.18   269.2 2118.11   328.4 2112.16   340.2 2109.35
   353.8 2107.16   376.7 2106.31   384.5 2105.45   392.5 2104.67   400.6 2104.84
   404.2 2105.43   415.7 2106.96   497.3 2110.08   533.8 2113.79   562.8 2114.59
   575.2 2116.33   579.3 2116.23   587.6  2117.1   612.4 2117.63   641.3 2120.33
   664.4 2123.86   690.1 2125.34   703.4 2125.33   732.3 2128.37   744.3 2128.11
#Mann= 7 ,-1,0
       0     .06       0     160     .05       0     200     .06       0
  368.43     .05       0   384.5    .045       0   404.2     .05       0
  468.43     .06       0
#XS Ineff= 2 , 0
             379 2110.29   409.6         2110.09
Permanent Ineff=
       F       F
Bank Sta=384.5,404.2
XS Rating Curve= 0 ,0
Exp/Cntr(USF)=0,0
Exp/Cntr=0.5,0.3

Type RM Length L Ch R = 1 ,4138    ,19.4,21.1,26.5
BEGIN DESCRIPTION:
structure xs 2; 9 ft between structure & xs
END DESCRIPTION:
XS GIS Cut Line= 5
2184127.93909907391120.774951549  2184288.654933390804.906754366
2184314.23438471390785.1782744162184331.32544547390683.409124382
2184266.67106544390394.064770204
#Sta/Elev= 30
       0 2139.43    26.6 2137.89    41.5 2136.01    53.4 2133.62    79.9 2131.14
   120.7 2130.53   192.5 2127.42     206 2127.99   231.9 2126.53   247.5  2126.6
   255.7 2125.79   309.2    2116   356.7 2112.69   373.6 2112.16     411 2108.31
  418.342104.636   426.6 2103.94     437 2104.52   443.5 2105.74   447.5 2107.86
   451.6 2108.74     480  2108.2   492.2 2110.28   529.1 2110.64   559.4 2111.85
   631.2 2116.44   655.2 2119.15   669.4 2119.76   695.4 2123.48   786.4 2133.31
#Mann= 5 ,-1,0
       0     .06       0  418.34    .045       0     437     .06       0
   619.9      .1       0   639.9     .06       0
#XS Ineff= 2 , 0
          415.34  2108.4     440          2108.4
Permanent Ineff=
       F       F
Bank Sta=418.34,437
XS Rating Curve= 0 ,0
Exp/Cntr(USF)=0,0
Exp/Cntr=0.5,0.3

Type RM Length L Ch R = 1 ,4117    ,54.5,50.8,43.1
BEGIN DESCRIPTION:
structure xs 1
END DESCRIPTION:
XS GIS Cut Line= 4
2184203.83794951391118.5065468372184329.50337528390791.776439829
2184365.98688599390660.435801279 2184365.1761413390387.214843309
#Sta/Elev= 30
       0 2147.18    35.7 2144.65    61.4 2141.66    91.4 2136.89   134.4  2135.2
   177.7 2134.56   224.3 2131.53   254.3 2127.15     280    2121   335.2 2111.32
   352.8 2109.95   373.5 2107.17   381.8 2104.58     386 2104.03     415 2103.89
   416.1    2104   427.5 2105.17   444.1 2105.41   460.7 2108.62   474.6 2108.87
   497.6 2114.44   525.6 2118.76   537.6 2119.21   561.6 2122.56   577.6 2123.58
   605.6 2126.76   621.6 2126.92     639 2128.58   696.4 2140.16   759.6 2150.08
#Mann= 7 ,-1,0
       0     .05       0      70     .06       0     270      .1       0
     280     .06       0     386    .045       0   416.1     .06       0
  586.38      .1       0
Bank Sta=386,416.1
XS Rating Curve= 0 ,0
Exp/Cntr(USF)=0,0
Exp/Cntr=0.3,0.1

Type RM Length L Ch R = 1 ,4066    ,156.7,159.6,163.8
XS GIS Cut Line= 4
 2184378.1564139391029.4418557722184389.94492984390825.469549286
2184390.74329947 390678.569537282184544.03026852390419.099407378
#Sta/Elev= 30
       0 2154.56    12.3 2152.59    28.3 2146.34    36.3 2145.38    44.3 2145.83
    60.4 2141.21     112 2132.92   144.5 2126.32   188.6 2119.33   220.6 2111.34
   232.6 2108.98   240.6 2107.66   260.6 2105.81   272.6 2105.39   280.6 2103.96
   308.6 2103.42     323 2103.93   328.6 2104.24   336.6 2107.49   348.6 2108.19
   357.5 2112.07   388.3 2120.71   424.8 2129.14   440.9 2130.93   479.9 2136.83
   510.8 2140.04     548 2146.47   616.1 2151.08   631.6 2152.56   652.6 2155.93
#Mann= 5 ,-1,0
       0      .1       0     170     .06       0   280.6    .045       0
     323     .06       0  371.21      .1       0
Bank Sta=280.6,323
XS Rating Curve= 0 ,0
Exp/Cntr(USF)=0,0
Exp/Cntr=0.3,0.1

Type RM Length L Ch R = 1 ,3906    ,264,258.5,252.2
XS GIS Cut Line= 2
2184456.63758338391114.7642760622184630.02912172390406.918819557
#Sta/Elev= 30
       0 2159.39    51.1 2160.98    75.8 2160.48    96.4 2158.79   125.2  2154.7
   145.8 2149.52   170.5 2140.21   186.2  2135.6   261.1 2118.57     294 2109.74
   314.6 2106.23   339.3    2104   347.6 2104.08   351.7 2103.49   359.9 2100.61
   364.8 2100.09   376.4 2100.42   384.6 2104.94   401.1 2105.56   409.3 2108.51
     421 2116.49   429.9 2119.93     452 2124.25   475.2 2129.84     536 2141.55
     603 2149.69   660.6 2154.57     677 2155.18   697.6 2157.96   728.8 2164.21
#Mann= 5 ,-1,0
       0      .1       0     270     .06       0   359.9    .045       0
   376.4     .06       0     470      .1       0
Bank Sta=359.9,376.4
XS Rating Curve= 0 ,0
Exp/Cntr(USF)=0,0
Exp/Cntr=0.3,0.1

Type RM Length L Ch R = 1 ,3648    ,258.6,259.3,259.7
XS GIS Cut Line= 2
2184857.09886271391133.1825826372184718.38563204390445.736130642
#Sta/Elev= 30
       0 2172.77   114.3 2165.06   126.5 2163.72     151 2159.31   175.5 2152.43
   183.6 2151.33   232.6 2137.16   252.1 2129.44     280 2116.52   289.7 2110.33
     302 2106.76   310.1 2101.27   318.3 2096.76   323.4 2094.91   330.5  2094.1
   340.3 2094.93   346.9 2096.62   350.9 2098.56     355 2099.34   367.3 2099.37
   383.6 2102.71   424.4 2117.13   453.8 2124.71   493.8 2132.02   540.7 2138.81
   567.2 2143.28   612.1 2147.54   624.3  2149.3   673.3 2152.64   701.3 2153.73
#Mann= 5 ,-1,0
       0      .1       0     280     .06       0   323.4    .045       0
   340.3     .06       0     480      .1       0
Bank Sta=323.4,340.3
XS Rating Curve= 0 ,0
Exp/Cntr(USF)=0,0
Exp/Cntr=0.3,0.1

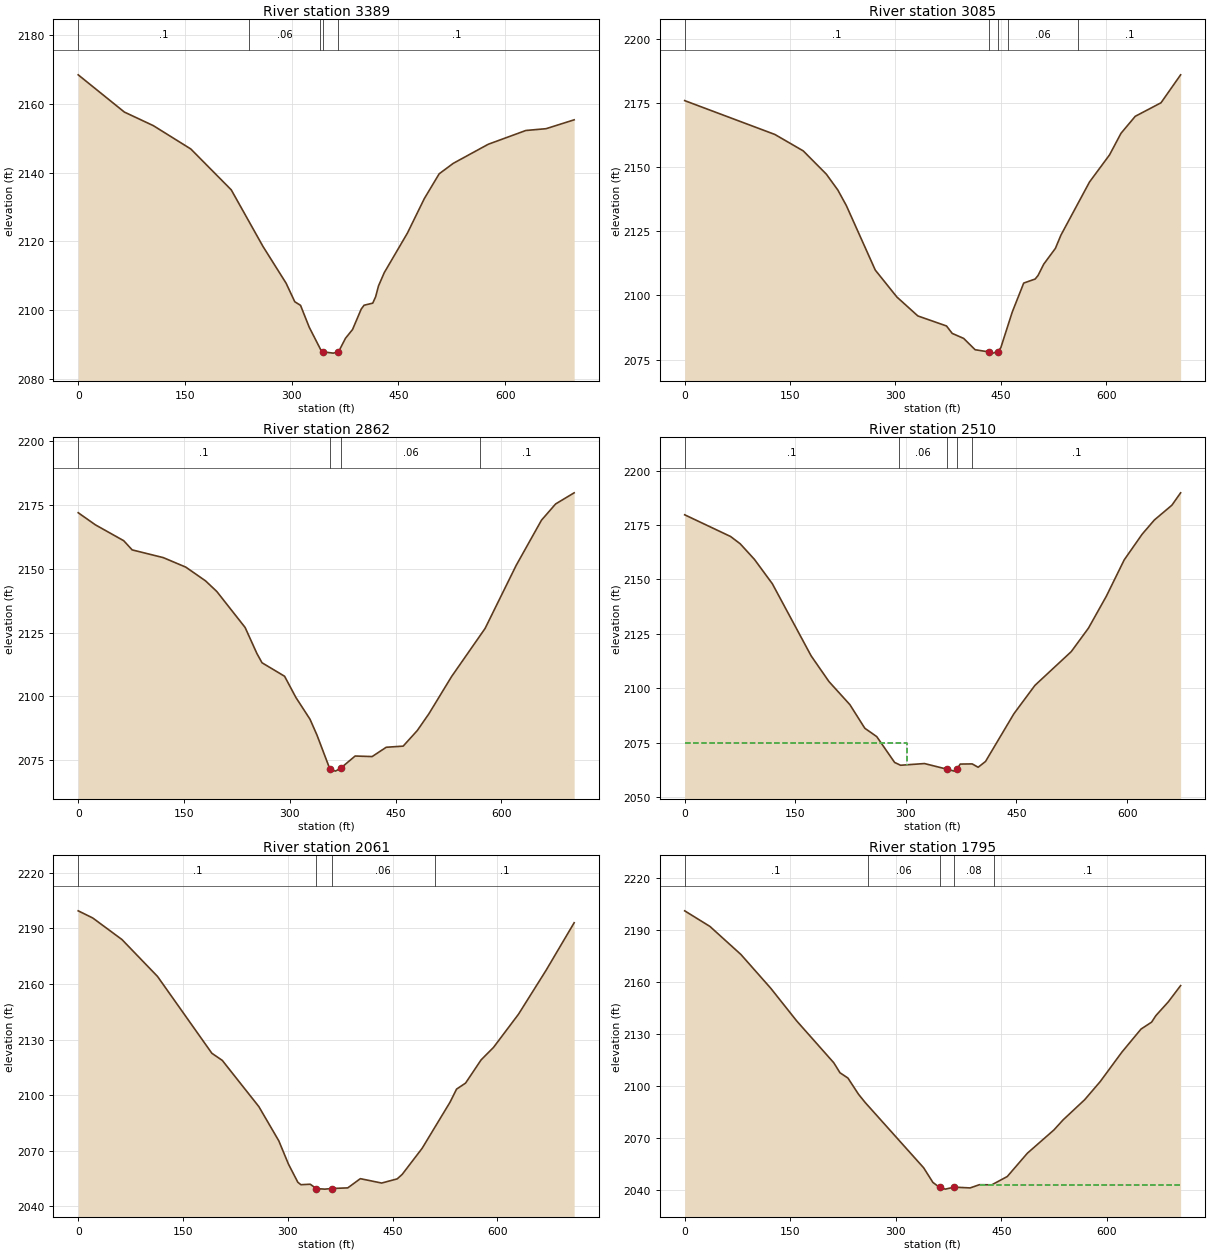
Type RM Length L Ch R = 1 ,3389    ,300,303.2,306.6
XS GIS Cut Line= 2
2185102.60227893391093.1092452162184983.61244222390406.281833306
#Sta/Elev= 30
       0 2168.44    64.9 2157.61   105.5 2153.68   158.3 2146.88   215.1 2135.01
   259.7 2118.56   292.2 2107.87   304.4 2102.48   312.5 2101.43   324.7 2095.08
   340.9 2088.52   344.6  2087.9   358.4 2087.54   365.7 2087.85   375.7 2091.86
   385.6  2094.4   397.8 2100.34   401.8 2101.46     414 2102.07   418.1 2103.94
   422.1 2107.08   430.2 2110.94   462.7 2122.42   486.5 2132.46   507.4 2139.67
   527.2 2142.71   576.3 2148.25   629.2 2152.26   657.6 2152.78   697.1 2155.36
#Mann= 5 ,-1,0
       0      .1       0     240     .06       0     340      .1       0
   344.6    .045       0   365.7      .1       0
Bank Sta=344.6,365.7
XS Rating Curve= 0 ,0
Exp/Cntr(USF)=0,0
Exp/Cntr=0.3,0.1

Type RM Length L Ch R = 1 ,3085    ,227.7,223.3,221.3
XS GIS Cut Line= 2
2185240.80378569391111.3145542472185373.39731501390417.748400899
#Sta/Elev= 30
       0 2175.93   128.4 2162.74   168.8 2156.34   201.7 2147.27     218 2141.11
   230.1 2135.07   271.4 2109.87   302.1  2099.4     332 2092.01   372.8  2088.1
   380.9 2085.21   397.2 2083.26   413.5 2078.85   433.9 2077.95   438.9 2077.52
   445.7 2078.15   450.1 2079.64   466.4 2093.54   482.7 2104.82     499  2106.4
   503.1 2107.77   511.2 2112.19   527.8 2118.34   535.7 2123.51   576.4 2144.22
   604.9 2154.78   621.2 2163.19   641.5 2169.81   678.2 2175.09   706.1 2185.98
#Mann= 5 ,-1,0
       0      .1       0   433.9    .045       0   445.7      .1       0
     460     .06       0     560      .1       0
Bank Sta=433.9,445.7
XS Rating Curve= 0 ,0
Exp/Cntr(USF)=0,0
Exp/Cntr=0.3,0.1

Type RM Length L Ch R = 1 ,2862    ,353.7,352.4,351
XS GIS Cut Line= 2
2185541.60430773391129.6007847422185517.64701086390426.938226091
#Sta/Elev= 30
       0 2171.88    24.4 2167.14    64.5 2160.94    76.5 2157.34   120.5 2154.33
   152.5  2150.6   180.5 2145.23   196.5 2141.06   236.6    2127   253.4 2116.76
   260.6 2113.18   292.6 2107.89   308.6 2099.61   328.6 2091.09   338.5 2084.89
   356.6 2071.74   364.6 2070.78   371.9 2071.88   392.6 2076.69   416.7 2076.48
   436.7 2080.12   460.7 2080.56   480.7 2086.66   497.2 2093.23   529.3 2107.77
   576.8 2126.59     621 2151.33   656.8 2168.97   676.8 2175.31   703.1 2179.67
#Mann= 4 ,-1,0
       0      .1       0   356.6    .045       0   371.9     .06       0
     570      .1       0
Bank Sta=356.6,371.9
XS Rating Curve= 0 ,0
Exp/Cntr(USF)=0,0
Exp/Cntr=0.3,0.1

Type RM Length L Ch R = 1 ,2510    ,450,448.6,439.9
XS GIS Cut Line= 2
2185922.43709259391046.7832647182185823.25248054390381.585918697
#Sta/Elev= 30
       0 2179.68    62.3  2169.7    75.3 2166.36    94.6  2159.2   118.9    2148
   171.5 2114.88   195.7 2103.06   224.1 2092.44   244.3 2081.62   260.5 2077.77
   284.7 2065.92   292.8 2064.62   325.2  2065.4   355.3 2062.85   365.6 2061.92
   369.4 2062.95   373.7 2065.16   389.9 2065.24     398  2063.7     408 2066.35
   446.5 2088.28     475 2101.31   524.3 2116.83   547.6  2127.6   571.9  2142.3
   596.1 2158.97   620.4 2170.75   636.9 2177.26   660.8  2184.1   672.6 2189.77
#Mann= 5 ,-1,0
       0      .1       0     290     .06       0   355.3    .045       0
   369.4     .06       0     390      .1       0
#XS Ineff= 2 , 0
          301.16 2074.68
Permanent Ineff=
       F       F
Bank Sta=355.3,369.4
XS Rating Curve= 0 ,0
Exp/Cntr(USF)=0,0
Exp/Cntr=0.3,0.1

Type RM Length L Ch R = 1 ,2061    ,264.6,265.6,264.9
XS GIS Cut Line= 2
2186425.07874549 390915.889739572186115.01387693  390277.4008984
#Sta/Elev= 30
       0  2199.5    20.8 2195.64    62.6 2184.01   113.5  2164.1   191.3 2122.63
   206.2 2118.79   258.5 2093.87   287.1 2075.38   300.9 2062.83   314.3 2053.05
   318.7 2051.71   332.1 2051.96   340.9 2049.61   340.9  2049.6   352.9 2049.32
   363.2 2049.65   385.8    2050   403.8 2054.96   434.3  2052.6   456.6 2054.86
   463.7 2057.28   492.2 2071.33   532.2 2096.26   541.5 2103.29   554.4 2106.54
   576.6 2119.05   594.4 2125.81     630 2143.63   669.6 2167.39   709.8 2193.06
#Mann= 4 ,-1,0
       0      .1       0   340.9    .045       0   363.2     .06       0
     510      .1       0
Bank Sta=340.9,363.2
XS Rating Curve= 0 ,0
Exp/Cntr(USF)=0,0
Exp/Cntr=0.3,0.1

Type RM Length L Ch R = 1 ,1795    ,334.6,334.5,334.8
XS GIS Cut Line= 2
2186647.14676679390797.8335698482186353.40110184390157.304828226
#Sta/Elev= 30
       0    2201    35.9    2192    79.9 2175.84   122.3 2156.37   159.1 2137.57
   211.9  2113.4   220.7 2107.65     232  2104.6     247 2095.28   256.6 2090.46
   339.6 2052.86   352.7 2044.45   362.2 2041.59   370.4 2040.58   382.9 2041.73
   405.6 2041.27   418.8 2043.13   436.4 2043.06   458.4 2047.85   486.9 2061.26
   524.7  2074.7   537.6 2080.45   568.4 2092.13   590.4 2102.55   621.2 2119.52
   648.4 2132.83   663.5 2136.84   669.6 2140.63   687.2 2148.53   704.7 2157.91
#Mann= 5 ,-1,0
       0      .1       0     260     .06       0   362.2    .045       0
   382.9     .08       0     440      .1       0
#XS Ineff= 2 , 0
                          419.57         2043.16
Permanent Ineff=
       F       F
Bank Sta=362.2,382.9
XS Rating Curve= 0 ,0
Exp/Cntr(USF)=0,0
Exp/Cntr=0.3,0.1