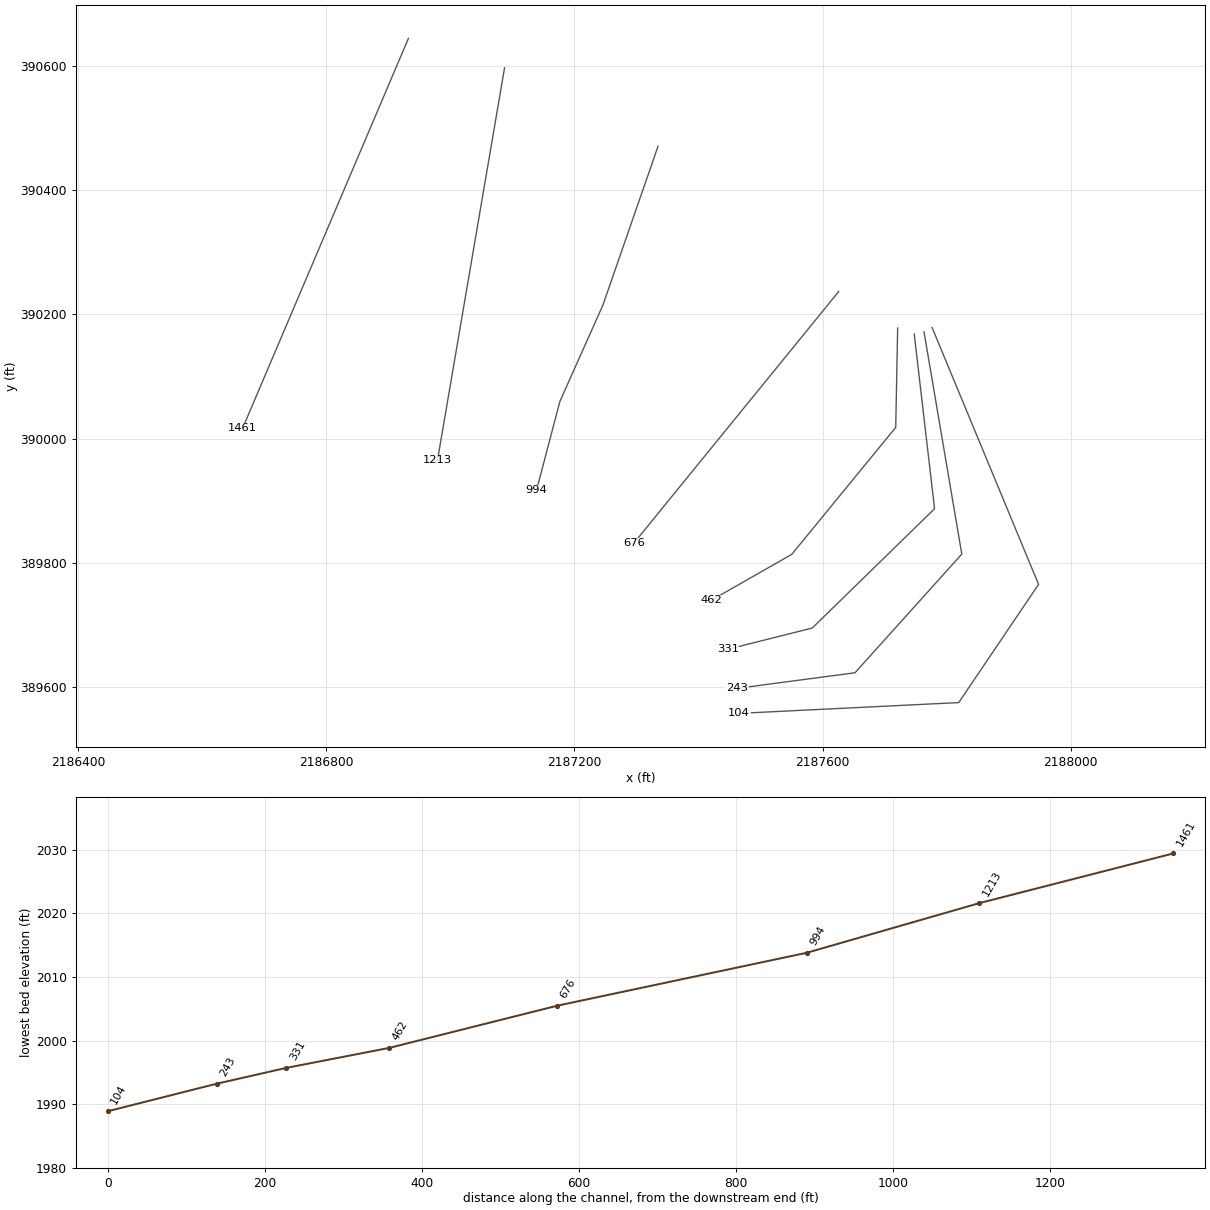
HEC-RAS study TRMPRN.prj: TRMPRN

--- TRMPRN.g01 (geometry) --- (continued)

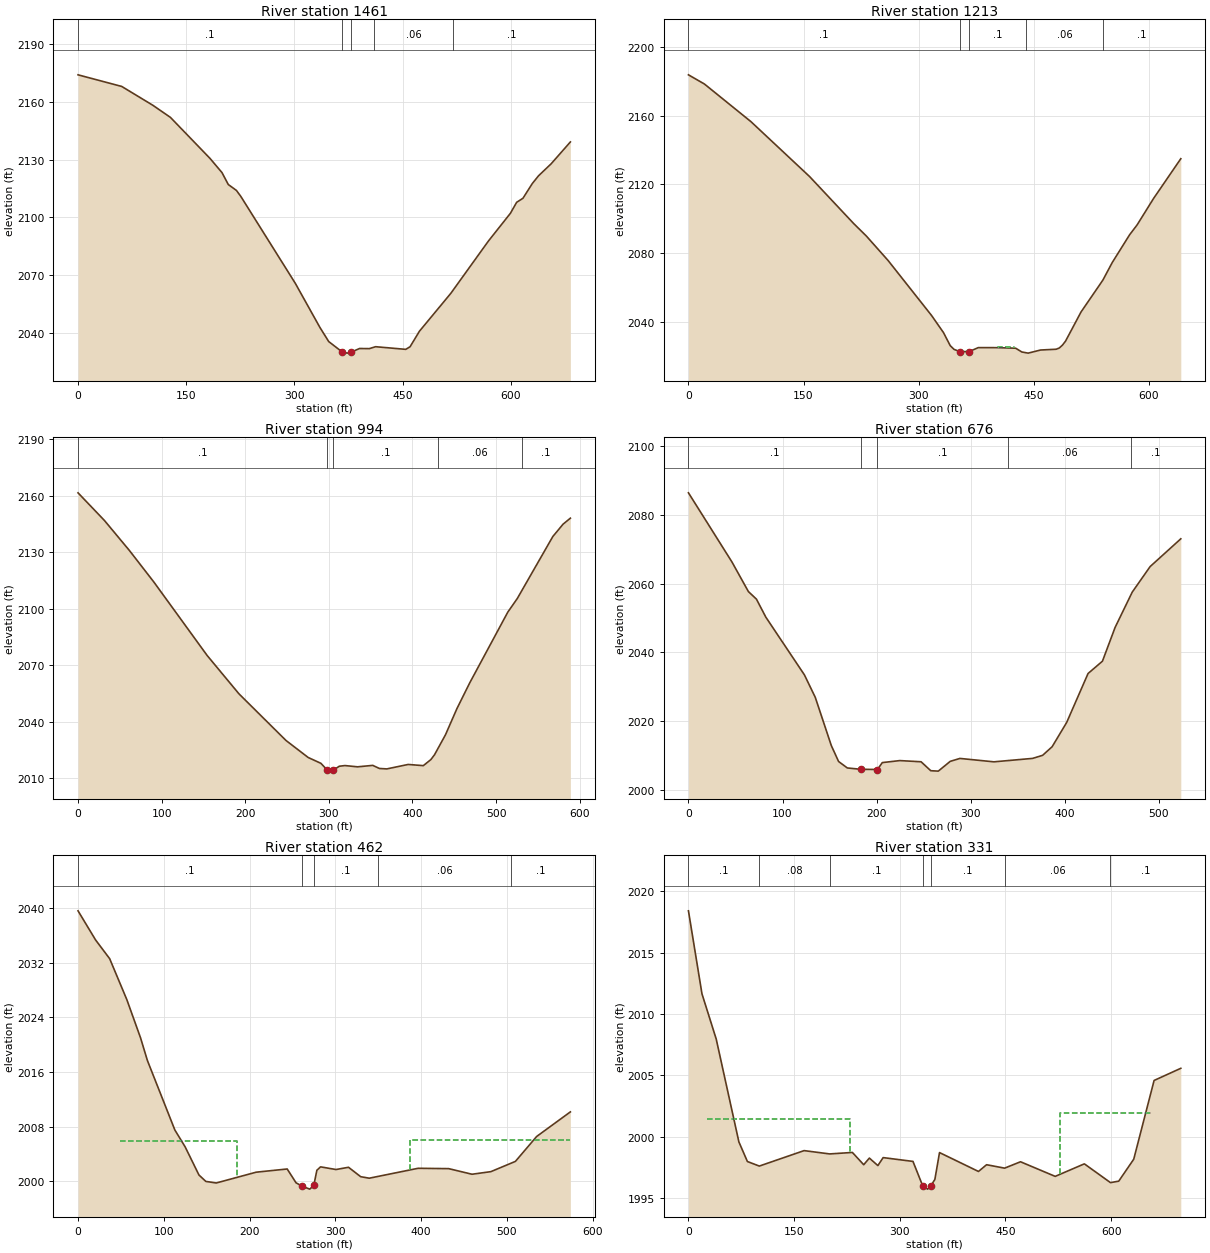
Type RM Length L Ch R = 1 ,1461    ,245.3,247.7,250.6
XS GIS Cut Line= 2
2186932.53693522390644.9193939042186665.30997614390016.630054989
#Sta/Elev= 30
       0 2174.13    60.6 2168.09   103.8 2158.29   128.2 2151.98   183.1 2130.64
   199.7 2123.26   208.4 2117.08   219.7 2114.01   225.7 2110.94   301.4 2065.67
   335.5 2042.75   347.7 2035.42     366 2030.13   373.5 2029.42   379.1 2029.98
   390.4 2031.82     404 2031.76   412.7 2032.76   454.5 2031.38   460.5 2032.75
   473.5 2040.82     517 2060.51   569.1 2087.68   599.6 2102.11   608.3 2107.84
     617 2109.93     630  2117.6   638.7 2121.65   656.1 2127.85   682.8 2139.23
#Mann= 5 ,-1,0
       0      .1       0     366    .045       0   379.1      .1       0
     410     .06       0     520      .1       0
Bank Sta=366,379.1
XS Rating Curve= 0 ,0
Exp/Cntr(USF)=0,0
Exp/Cntr=0.3,0.1

Type RM Length L Ch R = 1 ,1213    ,221.6,219.1,217.1
XS GIS Cut Line= 2
2187087.44486874390597.4122629932186979.33014484389965.043123175
#Sta/Elev= 30
       0 2183.72    20.8 2178.37    81.4 2156.46   157.8 2124.47   215.3 2097.07
   231.8  2089.8     260 2075.62   316.8  2043.5   332.3 2033.55   341.1 2025.93
   346.1 2023.76   353.6 2022.51   365.5 2022.46   377.6 2024.79     402 2024.78
   426.3 2024.46   434.4 2022.25   442.6 2021.59   458.8  2023.4   479.1 2023.86
   483.1 2024.56   487.2  2026.2   491.3 2028.56   511.5 2045.55     540 2064.15
   552.1 2074.31   574.8 2090.53   584.6  2096.3     606 2111.68   641.5 2134.85
#Mann= 5 ,-1,0
       0      .1       0   353.6    .045       0   365.5      .1       0
     440     .06       0     540      .1       0
#XS Ineff= 1 ,-1
  403.08  424.64  2024.9
Permanent Ineff=
       F
Bank Sta=353.6,365.5
XS Rating Curve= 0 ,0
Exp/Cntr(USF)=0,0
Exp/Cntr=0.3,0.1

Type RM Length L Ch R = 1 ,994     ,318.3,317.9,308.9
XS GIS Cut Line= 4
2187334.79136764390471.0484532892187245.92554022390214.994374287
2187176.64031885390059.8557264222187138.98530723389916.766682274
#Sta/Elev= 30
       0 2161.44    31.6 2146.76    61.3 2130.94    90.9    2114   154.4 2075.18
   192.5 2054.81   248.7 2030.09   275.3 2021.04   290.5 2017.95     298 2014.44
   299.3 2013.81   304.8 2014.21   312.5  2016.4   319.2 2016.76   334.4 2016.09
   352.5 2016.86   360.6 2015.21   369.4 2014.99   394.9 2017.35     413 2016.72
     422 2019.92   426.4 2022.49   439.5 2033.08   453.3 2047.06   468.5 2060.61
     514 2098.12   525.4 2105.37   567.9 2138.25   580.2 2144.83   588.9 2147.99
#Mann= 5 ,-1,0
       0      .1       0     298    .045       0   304.8      .1       0
  431.04     .06       0  530.94      .1       0
Bank Sta=298,304.8
XS Rating Curve= 0 ,0
Exp/Cntr(USF)=0,0
Exp/Cntr=0.3,0.1

Type RM Length L Ch R = 1 ,676     ,213.3,213.9,212.5
XS GIS Cut Line= 2
2187626.03779033390236.9784826412187295.57391726389831.038292888
#Sta/Elev= 30
       0 2086.35    46.2 2066.28    63.7 2057.67    72.3 2055.45    82.3 2050.21
   123.3 2033.45   134.8 2026.94   151.9  2012.9   159.6 2008.29   168.9 2006.41
   183.1 2006.03   200.9 2005.96   206.1 2007.97   224.7 2008.55   247.3 2008.21
   257.6 2005.61   265.6 2005.49   278.3 2008.33   288.6 2009.18   324.7 2008.19
   365.9 2009.19   376.5 2010.08   386.6 2012.57   402.1 2019.64   424.8 2033.85
   440.1 2037.43   453.6 2047.27   471.8 2057.51   490.8 2064.92   523.4 2072.99
#Mann= 5 ,-1,0
       0      .1       0   183.1    .045       0   200.9      .1       0
     340     .06       0     470      .1       0
Bank Sta=183.1,200.9
XS Rating Curve= 0 ,0
Exp/Cntr(USF)=0,0
Exp/Cntr=0.3,0.1

Type RM Length L Ch R = 1 ,462     ,131.7,131.1,129.6
XS GIS Cut Line= 4
2187720.96178276390178.1041672082187717.84394781390017.874561773
2187550.29420811389813.3174766592187420.51227094389739.215147735
#Sta/Elev= 30
       0 2039.61    20.5 2035.34    36.9  2032.6    56.9 2026.61    72.9 2021.01
    80.9 2017.69   112.9 2007.52   124.9 2005.05     141 2000.93     149 1999.99
   161.2 1999.76   207.7 2001.34   243.9 2001.81   254.2 1999.79   261.4 1999.28
   270.2 1998.86   274.9  1999.4   278.5 2001.62   282.8 2002.12   300.8 2001.73
   315.4 2002.06   329.6 2000.68   339.6 2000.46   396.5 2001.91   432.2 2001.86
   459.4 2001.04   481.4 2001.42     510 2002.92   534.8 2006.57   574.1 2010.17
#Mann= 5 ,-1,0
       0      .1       0   261.4    .045       0   274.9      .1       0
  350.26     .06       0  504.68      .1       0
#XS Ineff= 2 ,-1
   48.66  184.882005.902  386.82  661.192005.983
Permanent Ineff=
       F       F
Bank Sta=261.4,274.9
XS Rating Curve= 0 ,0
Exp/Cntr(USF)=0,0
Exp/Cntr=0.3,0.1

Type RM Length L Ch R = 1 ,331     ,87.8,88.7,89
XS GIS Cut Line= 4
2187747.68880132390168.2835168112187780.43584368389886.798301635
2187583.25684394389694.4965209712187447.39145543389660.355987447
#Sta/Elev= 30
       0 2018.41    19.2 2011.64    39.4 2007.96    71.6 1999.57    83.7 1997.97
   100.6  1997.6   164.2 1998.86   200.4 1998.59   232.7 1998.71   248.8 1997.71
   256.8 1998.25   268.9 1997.64   276.4 1998.29   318.7 1997.98   332.8 1995.95
   339.6 1995.72   344.1    1996   349.8 1996.51   356.4  1998.7   411.7 1997.16
   423.2 1997.71   448.8 1997.43   471.4 1997.95   520.6 1996.76     562 1997.78
   599.1 1996.25   610.8 1996.37   632.1 1998.16     661 2004.58   698.9 2005.57
#Mann= 7 ,-1,0
       0      .1       0   100.6     .08       0   200.4      .1       0
   332.8    .045       0   344.1      .1       0   448.8     .06       0
   599.1      .1       0
#XS Ineff= 2 ,-1
   26.03  229.13 2001.41     528  658.042001.956
Permanent Ineff=
       F       F
Bank Sta=332.8,344.1
XS Rating Curve= 0 ,0
Exp/Cntr(USF)=0,0
Exp/Cntr=0.3,0.1

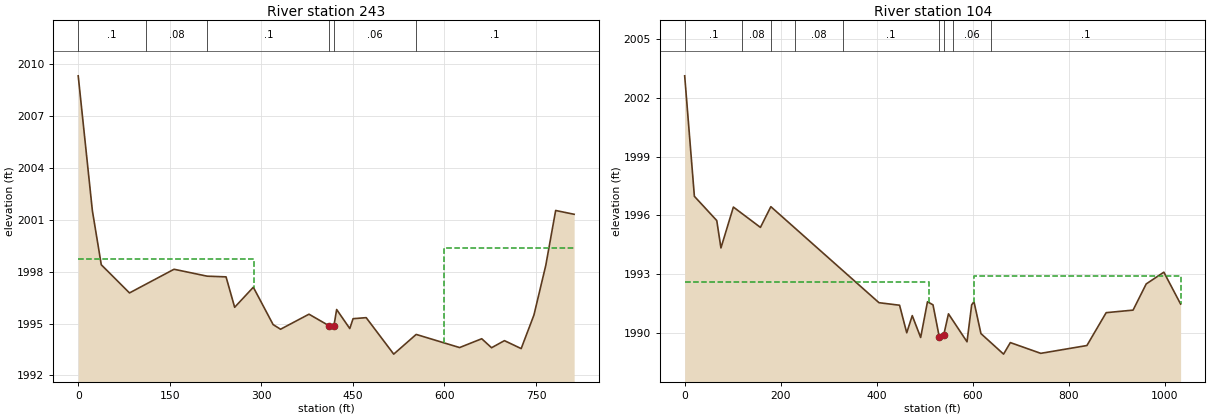
Type RM Length L Ch R = 1 ,243     ,138.6,138.6,138.6
XS GIS Cut Line= 4
2187763.40730128390172.0016198912187824.31692709389813.696530083
2187652.13779081389622.442745329 2187462.0372088389597.283308735
#Sta/Elev= 30
       0 2009.33    23.2 2001.53    37.8  1998.4      84 1996.77   110.6 1997.27
     157 1998.14   211.2 1997.74   242.2  1997.7   256.3 1995.94   286.9  1997.1
   319.3 1994.94   331.5 1994.67   378.1 1995.54   411.5 1994.86  418.95 1994.87
   423.4 1995.81   444.9 1994.71   450.3 1995.28   471.8 1995.34   516.9 1993.23
   553.7 1994.37   624.8 1993.61   661.1 1994.12   677.2  1993.6   698.3 1994.01
   725.7 1993.55   746.6 1995.49     766 1998.36   782.2 2001.54   812.5 2001.32
#Mann= 6 ,-1,0
       0      .1       0   110.6     .08       0   211.2      .1       0
   411.5    .045       0  418.95     .06       0   553.7      .1       0
#XS Ineff= 2 , 0
          287.32 1998.76     600         1999.35
Permanent Ineff=
       F       F
Bank Sta=411.5,418.95
XS Rating Curve= 0 ,0
Exp/Cntr(USF)=0,0
Exp/Cntr=0.3,0.1

Type RM Length L Ch R = 1 ,104     ,,,
XS GIS Cut Line= 4
2187776.42602789390178.8866412492187948.05237757389764.852921027
2187819.36816649389574.4087810792187465.34912922 389557.00669648
#Sta/Elev= 30
       0 2003.14    20.2 1996.98    66.8 1995.74    75.5 1994.34   101.4 1996.43
   157.7 1995.39   179.4 1996.45   404.5 1991.54   447.4 1991.41   462.3    1990
   473.8 1990.88   491.3 1989.76   505.5 1991.59     517 1991.43   529.9 1989.81
   539.5 1989.91   549.2 1990.97   587.8 1989.54   597.5 1991.43   602.3 1991.59
   616.8 1989.96   663.9 1988.91     678  1989.5   741.3 1988.95   837.4 1989.35
   877.5 1991.03   933.5 1991.16   960.9  1992.5   997.6  1993.1  1032.5 1991.47
#Mann= 9 ,-1,0
       0      .1       0     120     .08       0     180      .1       0
     230     .08       0     330      .1       0   529.9    .045       0
   539.5      .1       0   558.2     .06       0   638.2      .1       0
#XS Ineff= 2 , 0
          508.76 1992.62  602.76         1992.88
Permanent Ineff=
       F       F
Bank Sta=529.9,539.5
XS Rating Curve= 0 ,0
Exp/Cntr(USF)=0,0
Exp/Cntr=0.3,0.1
LCMann Table=0

Chan Stop Cuts=-1
Use User Specified Reach Order=0
Composite Channel Slope=5